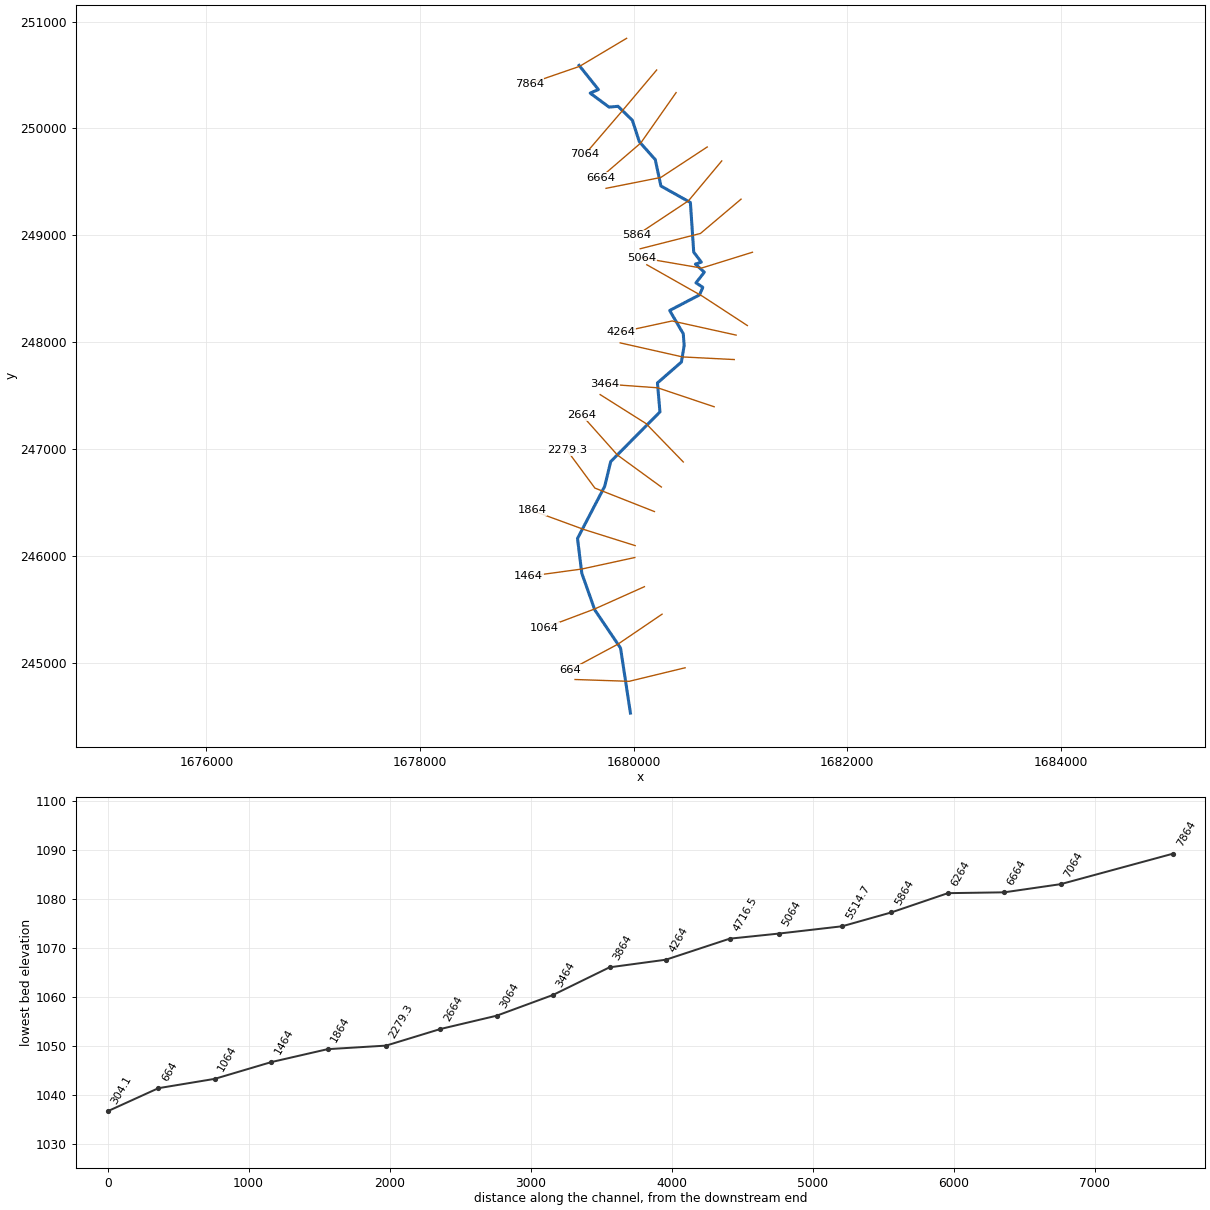
--- StutlrFk.prj (project) ---

Proj Title=StutlrFk
Current Plan=p01
Geom File=g01
Flow File=f01
Plan File=p01
DSS Export Rating Curves=0
DSS Export Rating Curve Sorted=0
DSS Export Volume Flow Curves=0
DXF OffsetX=0
DXF OffsetY=0
DXF ScaleX=0
DXF ScaleY=0

--- StutlrFk.p01 (plan) ---

Plan Title=Floodplain
Program Version=4.00
Geom File=g01
Flow File=f01
K Sum by GR=0
Std Step Tol=0.01
Critical Tol=0.01
Num of Std Step Trials=20
Max Error Tol=0.3
Flow Tol Ratio=0.001
Split Flow NTrial=30
Split Flow Tol=0.02
Split Flow Ratio=0.02
Log Output Level=0
Friction Slope Method=1
Unsteady Friction Slope Method=2
Unsteady Bridges Friction Slope Method=1
Global Log Level=0
CheckData=False
Run HTab=0
Run UNet=0
Run PostProcess=0
UNET Theta=0
UNET Theta Warmup=0
UNET ZTol=0
UNET ZSATol=0
UNET MxIter=0
UNET MaxInSteps=0
UNET DtIC=0
UNET DtMin=0
UNET MaxCRTS=0
UNET WFStab=0
UNET SFStab=0
UNET WFX=0
UNET SFX=0
UNET DSS MLevel=0
UNET DZMax Abort=0
UNET Convert EG Bridges=0
UNET Use Existing IB Tables=0
UNET Froude Limit=0
UNET Froude Power=0
Write IC File=0
Echo Input=False
Echo Output=False
Write Detailed=0

--- StutlrFk.f01 (steady flow) ---

Flow Title=NFF Regression Equation
Program Version=4.00
Number of Profiles=1
Profile Names=P100yr
River Rch & RM=StutlrFk,Main      ,7864
726.2800
River Rch & RM=StutlrFk,Main      ,5514.7
788.5428
River Rch & RM=StutlrFk,Main      ,5064
903.9883
River Rch & RM=StutlrFk,Main      ,2279.3
965.1096
River Rch & RM=StutlrFk,Main      ,1864
1070.265
River Rch & RM=StutlrFk,Main      ,304.1
1096.266
Boundary for River Rch & Prof#=StutlrFk,Main      ,1
Up Type=0
Dn Type=3
Dn Slope=0.006837

--- StutlrFk.g01 (geometry) ---

Geom Title=USGS 3m DEM
Program Version=4.00

River Reach=StutlrFk     ,Main
Reach XY= 30
     1679489.813      250589.499     1679670.581      250363.728
     1679593.236      250330.194     1679770.606      250199.242
     1679853.891      250207.022     1679987.950      250076.587
     1680053.934      249875.116     1680202.632      249708.399
     1680255.600      249461.583     1680531.540      249307.227
     1680562.721      248843.019     1680633.607      248749.775
     1680578.285      248731.406     1680661.835      248655.551
     1680583.998      248556.091     1680647.793      248514.069
     1680617.136      248443.221     1680337.728      248297.468
     1680464.623      248080.104     1680473.313      247970.363
     1680447.407      247814.844     1680223.316      247620.078
     1680246.460      247348.816     1679785.645      246884.051
     1679729.556      246653.269     1679474.793      246164.924
     1679515.395      245838.472     1679636.689      245496.556
     1679877.611      245140.556     1679970.189      244532.594

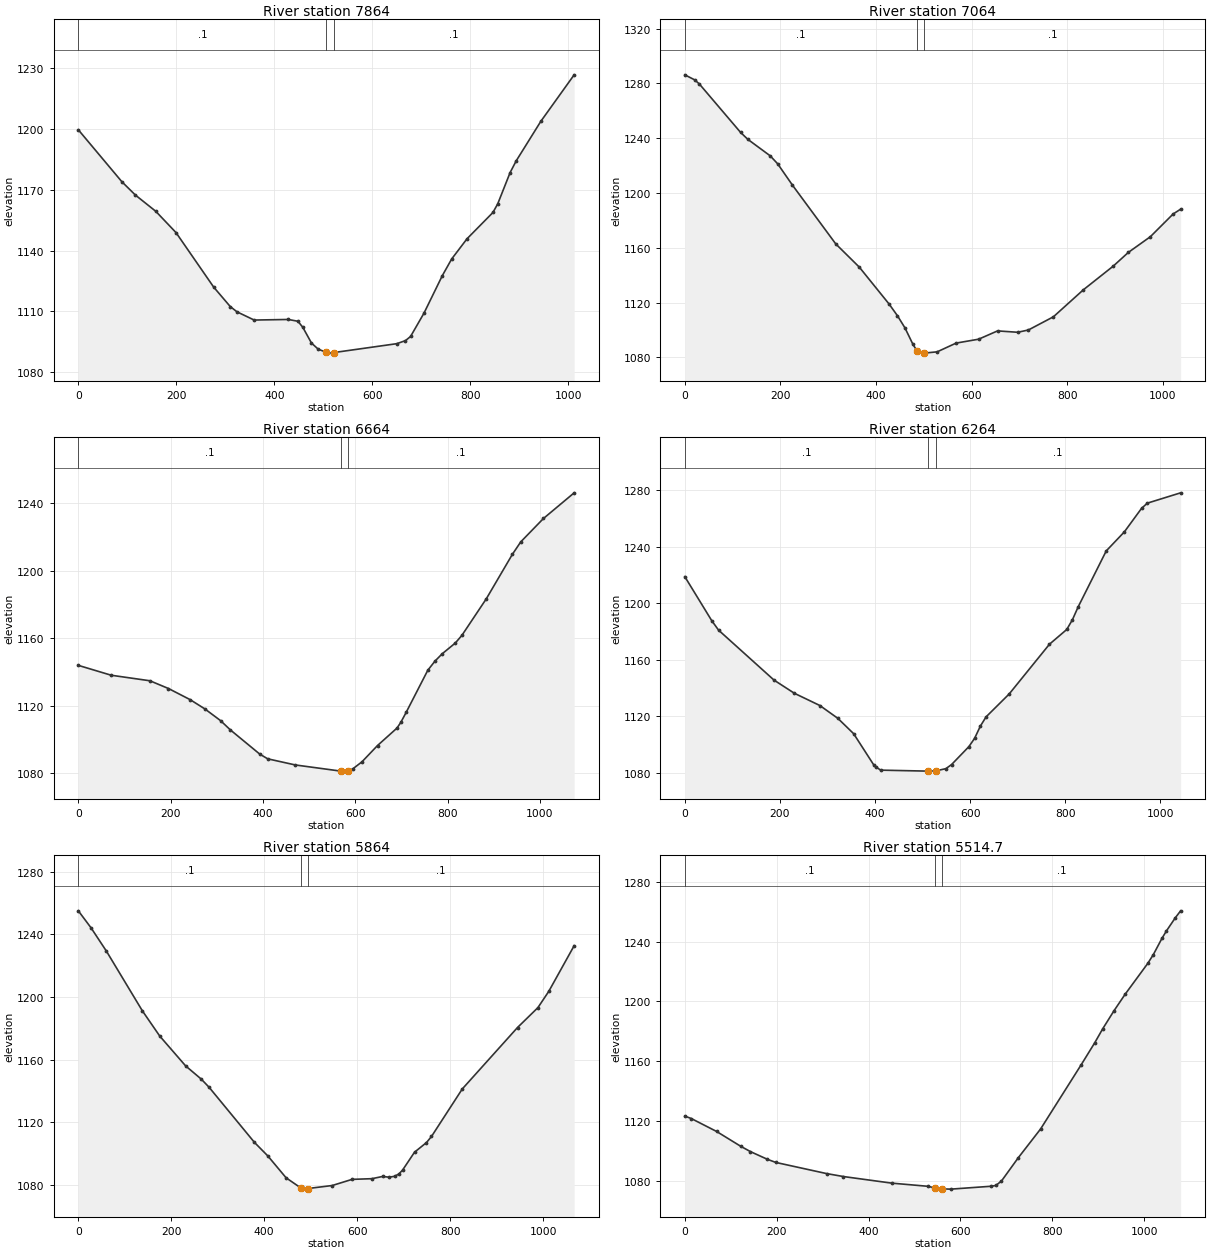
Type RM Length L Ch R = 1 ,7864,728.686,800,778.637
XS GIS Cut Line= 3
     1679934.329      250842.770     1679493.069      250580.044
     1679022.015      250417.847
#Sta/Elev= 30
       0 1199.66    88.8 1174.01   116.4 1167.42   157.9 1159.42   199.3 1148.88
   276.2 1121.93   309.9 1112.35   323.7 1109.73   358.8 1105.66   428.4 1105.95
   448.1 1105.06   458.0 1102.09   475.7 1094.31   489.5 1091.26   506.1 1089.72
   516.8 1089.32   521.1 1089.59   649.8 1093.99   667.5 1095.50   677.9 1097.55
   705.2 1109.04   742.8 1127.65   761.9 1135.88   793.1 1145.82   846.0 1158.82
   855.8 1163.10   881.0 1178.52   893.5 1184.34   943.7 1203.85  1011.7 1226.82
#Mann= 3 , 0 , 0
       0     0.1       0   506.1   0.045       0   521.1     0.1       0
Bank Sta=   506.1,   521.1
Exp/Cntr=0.3,0.1

Type RM Length L Ch R = 1 ,7064,369.042,400,376.953
XS GIS Cut Line= 3
     1680215.808      250546.501     1679898.241      250169.649
     1679543.708      249756.976
#Sta/Elev= 30
       0 1286.19    20.9 1282.47    30.7 1279.41   116.5 1244.23   131.8 1239.10
   178.6 1227.07   194.2 1221.25   225.2 1205.64   315.7 1162.78   365.0 1145.80
   427.1 1118.95   444.7 1110.36   460.4 1101.49   477.2 1089.41   485.3 1084.88
   499.9 1083.06   500.3 1083.06   527.8 1084.01   567.4 1090.38   614.4 1093.22
   654.1 1099.29   696.2 1098.28   718.5 1099.95   770.9 1109.59   833.5 1129.29
   896.1 1146.60   927.4 1156.53   973.6 1168.03  1021.3 1184.64  1036.9 1188.13
#Mann= 3 , 0 , 0
       0     0.1       0   485.3   0.045       0   500.3     0.1       0
Bank Sta=   485.3,   500.3
Exp/Cntr=0.3,0.1

Type RM Length L Ch R = 1 ,6664,423.824,400,397.83
XS GIS Cut Line= 3
     1680397.644      250335.017     1680066.924      249863.823
     1679688.858      249539.028
#Sta/Elev= 30
       0 1143.92    71.3 1138.08   155.1 1134.81   195.3 1130.23   242.1 1123.67
   274.0 1118.20   308.1 1111.25   329.2 1105.80   393.3 1091.39   410.3 1088.66
   470.0 1085.04   568.2 1081.41   575.7 1081.39   583.2 1081.51   594.0 1082.62
   614.4 1086.88   648.1 1096.52   690.2 1106.82   698.6 1110.22   710.2 1116.14
   757.1 1141.06   772.8 1146.50   788.5 1150.83   816.5 1157.09   830.9 1161.65
   883.8 1183.29   940.2 1209.53   958.4 1216.93  1007.6 1230.76  1074.1 1245.93
#Mann= 3 , 0 , 0
       0     0.1       0   568.2   0.045       0   583.2     0.1       0
Bank Sta=   568.2,   583.2
Exp/Cntr=0.3,0.1

Type RM Length L Ch R = 1 ,6264,395.704,400,398.659
XS GIS Cut Line= 3
     1680689.132      249826.610     1680254.580      249541.422
     1679741.947      249439.827
#Sta/Elev= 30
       0 1218.84    56.8 1187.60    71.0 1180.98   187.5 1145.65   230.4 1136.30
   284.0 1127.64   321.8 1118.56   355.0 1107.70   397.6 1085.44   401.9 1084.16
   411.8 1081.92   511.3 1081.22   512.3 1081.22   527.3 1081.38   548.8 1082.95
   560.9 1085.89   597.2 1098.54   609.3 1104.44   621.4 1113.08   633.4 1119.61
   682.0 1135.83   766.7 1171.03   803.0 1181.45   814.9 1188.32   827.2 1197.59
   886.0 1237.03   924.0 1250.47   960.3 1267.16   972.4 1270.83  1042.4 1278.14
#Mann= 3 , 0 , 0
       0     0.1       0   512.3   0.045       0   527.3     0.1       0
Bank Sta=   512.3,   527.3
Exp/Cntr=0.3,0.1

Type RM Length L Ch R = 1 ,5864,363.702,349.239,363.131
XS GIS Cut Line= 3
     1680825.262      249696.379     1680513.476      249323.137
     1680029.477      249002.444
#Sta/Elev= 30
       0 1255.01    27.2 1244.22    60.4 1229.28   137.7 1191.19   175.3 1174.99
   230.9 1155.98   264.4 1147.58   281.3 1142.36   379.0 1107.12   407.7 1098.50
   447.1 1084.51   478.8 1078.04   489.3 1077.29   493.8 1077.67   546.2 1079.59
   589.0 1083.52   631.7 1083.96   654.8 1085.38   668.3 1084.93   680.5 1085.46
   689.8 1086.99   697.7 1089.45   723.4 1100.87   749.1 1107.02   759.9 1110.91
   826.2 1141.27   945.0 1180.49   988.9 1193.19  1012.2 1203.55  1066.9 1232.75
#Mann= 3 , 0 , 0
       0     0.1       0   478.8   0.045       0   493.8     0.1       0
Bank Sta=   478.8,   493.8
Exp/Cntr=0.3,0.1

Type RM Length L Ch R = 1 ,5514.7,388.284,450.762,344.505
XS GIS Cut Line= 3
     1681005.638      249338.583     1680625.642      249017.697
     1680061.780      248874.601
#Sta/Elev= 30
       0 1123.34    14.1 1121.69    69.3 1113.02   121.5 1103.16   142.9 1099.55
   179.7 1094.41   198.1 1092.31   308.5 1084.86   345.3 1082.87   450.1 1078.47
   529.9 1076.32   544.5 1075.15   559.5 1074.60   579.4 1074.45   667.3 1076.39
   676.8 1076.89   689.1 1079.83   725.7 1095.42   774.4 1114.73   862.7 1157.67
   892.0 1172.29   909.6 1181.77   934.1 1193.81   958.6 1204.97  1007.6 1225.49
  1019.8 1231.42  1038.5 1242.28  1048.3 1247.26  1067.8 1256.13  1079.1 1260.67
#Mann= 3 , 0 , 0
       0     0.1       0   544.5   0.045       0   559.5     0.1       0
Bank Sta=   544.5,   559.5
Exp/Cntr=0.3,0.1

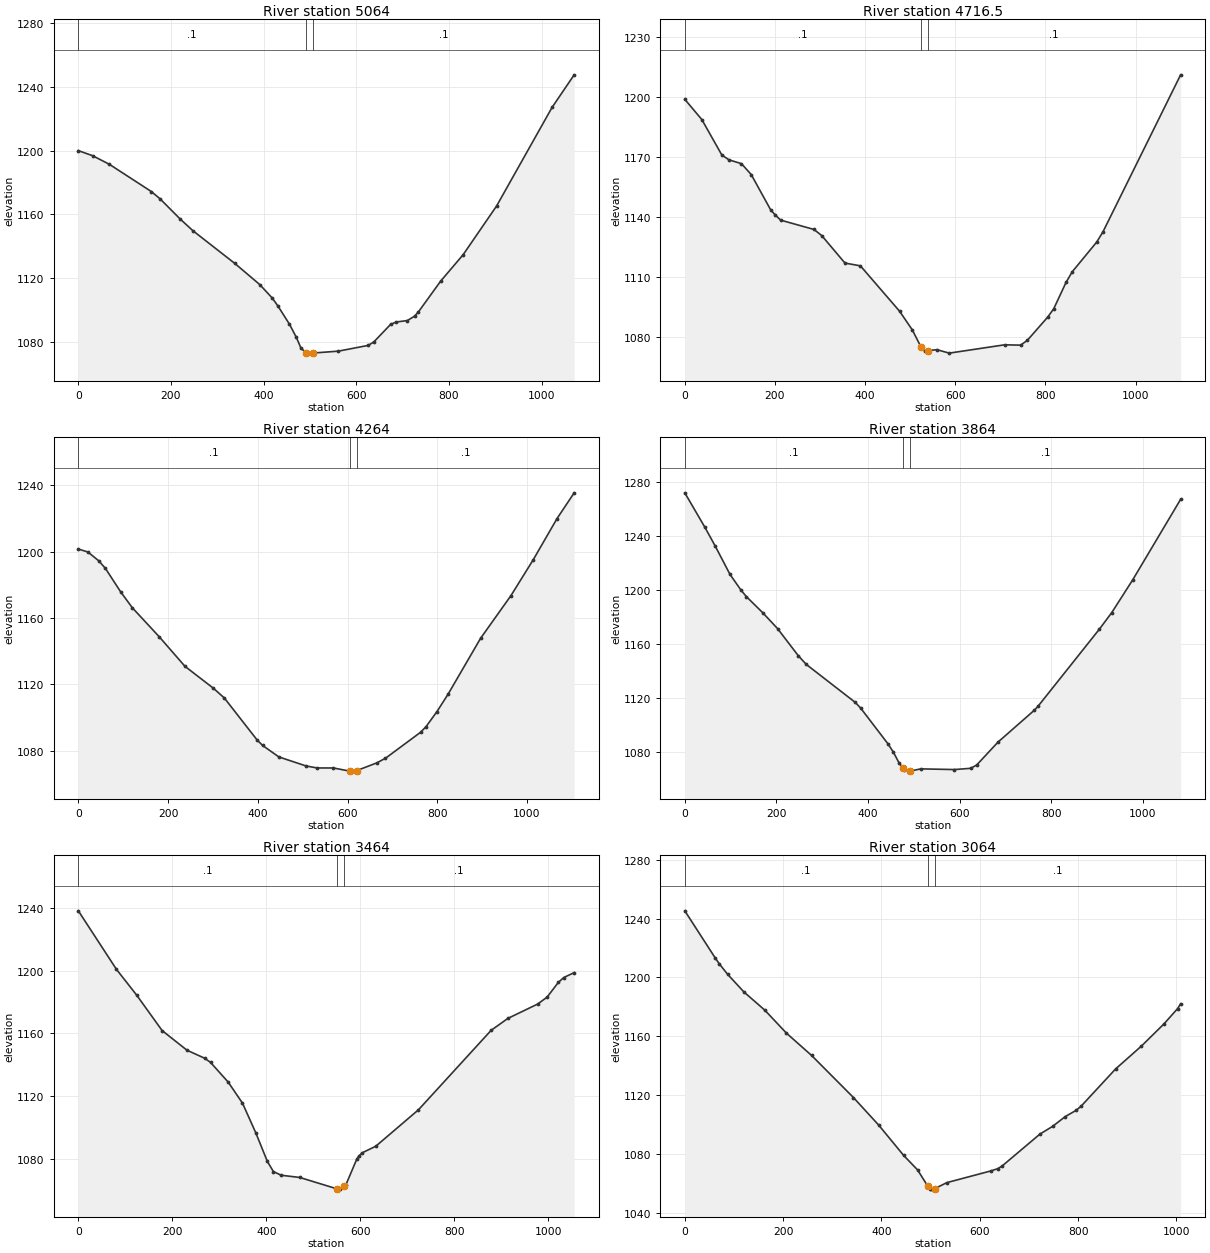
Type RM Length L Ch R = 1 ,5064,323.668,347.508,374.727
XS GIS Cut Line= 3
     1681112.557      248842.207     1680635.936      248694.094
     1680072.984      248790.686
#Sta/Elev= 30
       0 1199.93    30.8 1196.75    66.9 1191.37   157.5 1174.29   176.6 1169.66
   219.6 1157.11   247.2 1149.74   337.9 1129.17   391.5 1115.97   418.5 1107.53
   431.0 1102.44   455.8 1091.08   470.7 1082.77   480.7 1076.01   491.6 1073.29
   499.1 1072.95   506.6 1073.00   561.2 1074.19   625.8 1077.80   637.9 1079.97
   674.0 1090.96   686.1 1092.46   710.2 1093.38   725.7 1096.08   734.2 1098.83
   782.4 1118.20   830.6 1134.64   902.9 1165.23  1022.6 1227.03  1070.3 1247.46
#Mann= 3 , 0 , 0
       0     0.1       0   491.6   0.045       0   506.6     0.1       0
Bank Sta=   491.6,   506.6
Exp/Cntr=0.3,0.1

Type RM Length L Ch R = 1 ,4716.5,450.977,452.492,470.373
XS GIS Cut Line= 3
     1681064.619      248156.672     1680645.464      248430.070
     1680123.552      248725.149
#Sta/Elev= 30
       0 1199.01    37.8 1188.86    82.2 1171.12    97.9 1168.71   125.7 1166.78
   147.4 1161.32   190.9 1143.50   200.8 1141.09   212.6 1138.51   286.6 1133.84
   303.8 1130.78   355.3 1117.01   389.6 1115.62   476.7 1092.84   504.8 1083.52
     524 1074.98   532.1 1073.08     539 1073.18   559.4 1073.63   586.7 1071.91
   709.4 1076.07   745.1 1075.91   759.9 1078.31   804.9 1089.89   818.5 1094.14
   845.8 1107.33   859.5 1112.63   914.0 1127.58   927.6 1132.60  1100.0 1211.27
#Mann= 3 , 0 , 0
       0     0.1       0     524   0.045       0     539     0.1       0
Bank Sta=     524,     539
Exp/Cntr=0.3,0.1

Type RM Length L Ch R = 1 ,4264,382.798,400,385.886
XS GIS Cut Line= 3
     1680959.388      248067.244     1680360.482      248199.424
     1679879.883      248095.347
#Sta/Elev= 30
       0 1201.48    21.4 1199.70    45.8 1194.32    60.5 1189.77    94.4 1175.67
   120.3 1166.11   180.1 1148.67   237.7 1130.78   301.1 1117.56   325.4 1111.71
   398.4 1086.40   410.5 1083.14   447.0 1076.16   507.8 1070.71   532.1 1069.52
   568.6 1069.51   605.0 1067.61   605.8 1067.65   620.8 1067.97   664.6 1072.51
   684.6 1075.37   763.0 1091.08   775.1 1094.47   799.4 1103.53   824.4 1114.13
   896.6 1147.71   964.2 1173.41  1014.1 1195.13  1066.7 1219.77  1105.1 1235.38
#Mann= 3 , 0 , 0
       0     0.1       0   605.8   0.045       0   620.8     0.1       0
Bank Sta=   605.8,   620.8
Exp/Cntr=0.3,0.1

Type RM Length L Ch R = 1 ,3864,407.928,400,403.52
XS GIS Cut Line= 3
     1680942.081      247838.527     1680458.789      247862.959
     1679874.765      247994.324
#Sta/Elev= 30
       0 1272.00    44.0 1246.42    66.6 1232.48    98.7 1211.63   122.5 1200.10
   134.4 1195.21   170.1 1183.30   202.4 1171.58   247.6 1151.55   265.2 1145.03
   372.2 1116.91   384.0 1112.68   443.5 1086.28   455.4 1080.10   467.3 1072.43
   476.4 1068.22   479.2 1066.87   491.2 1066.05   491.4 1066.07   515.5 1067.72
   588.6 1067.21   624.2 1068.14   637.2 1070.57   683.8 1087.53   763.3 1111.17
   771.1 1114.02   905.0 1171.05   932.2 1183.39   978.0 1207.66  1082.5 1267.19
#Mann= 3 , 0 , 0
       0     0.1       0   476.4   0.045       0   491.4     0.1       0
Bank Sta=   476.4,   491.4
Exp/Cntr=0.3,0.1

Type RM Length L Ch R = 1 ,3464,409.177,400,388.68
XS GIS Cut Line= 3
     1680754.022      247396.938     1680225.004      247574.352
     1679729.428      247609.981
#Sta/Elev= 30
       0 1238.46    81.0 1201.06   124.1 1184.53   178.2 1161.87   231.2 1149.27
   268.8 1144.15   281.3 1141.48   318.9 1128.85   349.2 1115.43   377.3 1096.57
   402.2 1078.10   414.9 1071.67   431.6 1069.29   471.1 1067.87   550.5 1060.56
   556.8 1060.41   565.5 1062.33   568.8 1062.90   592.6 1079.76   597.5 1081.75
   604.5 1083.74   632.8 1087.85   723.5 1111.14   878.3 1162.04   914.0 1169.67
   977.1 1178.80   997.3 1183.26  1021.1 1192.66  1032.6 1195.76  1054.8 1198.93
#Mann= 3 , 0 , 0
       0     0.1       0   550.5   0.045       0   565.5     0.1       0
Bank Sta=   550.5,   565.5
Exp/Cntr=0.3,0.1

Type RM Length L Ch R = 1 ,3064,396.185,400,393.551
XS GIS Cut Line= 3
     1680465.078      246880.572     1680115.662      247240.364
     1679686.779      247510.884
#Sta/Elev= 30
       0 1245.31    62.1 1213.17    70.4 1209.19    87.4 1202.06   120.2 1190.20
   162.8 1177.79   206.7 1162.20   257.8 1147.06   343.0 1118.43   394.2 1099.77
   445.3 1079.03   473.5 1069.24     494 1058.31   498.7 1056.17   500.9 1056.16
     509 1056.56   533.0 1060.58   623.6 1068.62   636.3 1070.04   644.9 1071.71
   722.4 1093.57   748.2 1098.82   774.0 1105.49   795.7 1109.63   806.1 1112.50
   876.3 1137.84   929.0 1153.43   974.6 1168.42  1002.6 1178.91  1008.6 1182.12
#Mann= 3 , 0 , 0
       0     0.1       0     494   0.045       0     509     0.1       0
Bank Sta=     494,     509
Exp/Cntr=0.3,0.1

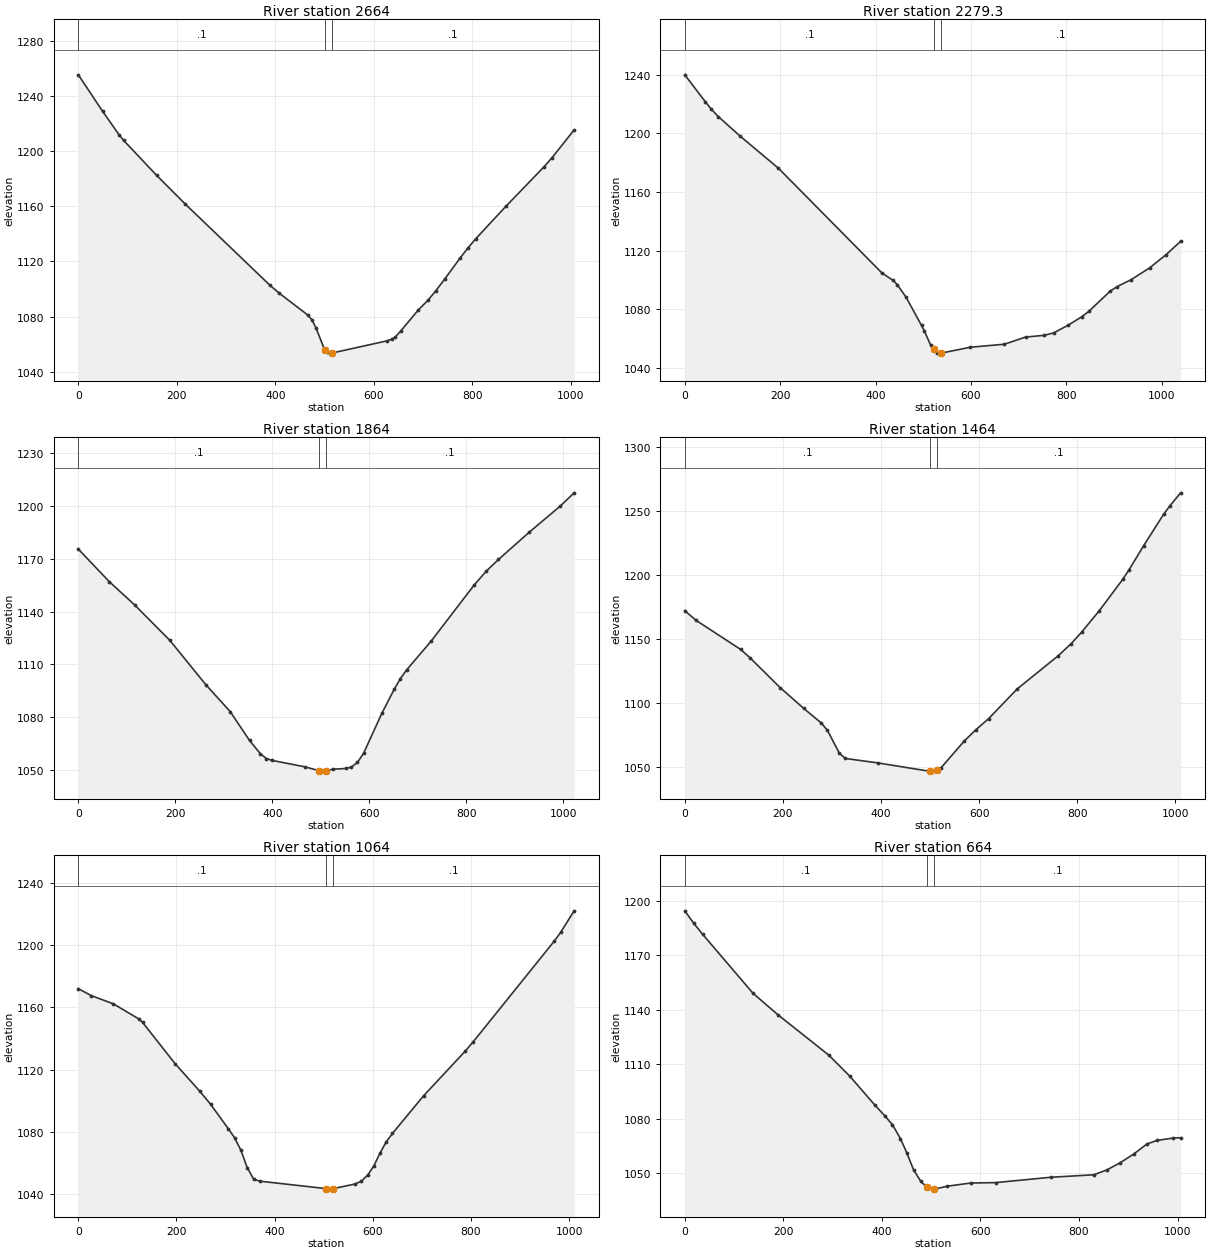
Type RM Length L Ch R = 1 ,2664,378.826,384.704,395.492
XS GIS Cut Line= 3
     1680259.625      246646.489     1679849.198      246944.981
     1679516.560      247317.459
#Sta/Elev= 30
       0 1255.32    49.3 1228.85    83.3 1211.54    91.8 1207.84   158.9 1182.42
   217.6 1161.41   389.3 1102.59   408.5 1096.76   465.8 1081.11   474.3 1077.58
   482.8 1071.59     500 1055.94   504.3 1054.56   512.0 1053.43     515 1053.50
   626.0 1062.25   636.8 1063.60   642.8 1064.78   654.6 1069.43   690.3 1084.68
   710.1 1091.83   725.9 1098.64   743.7 1107.01   775.5 1122.50   791.5 1129.87
   807.4 1136.55   868.5 1160.01   945.5 1188.53   962.4 1195.34  1006.9 1215.41
#Mann= 3 , 0 , 0
       0     0.1       0     500   0.045       0     515     0.1       0
Bank Sta=     500,     515
Exp/Cntr=0.3,0.1

Type RM Length L Ch R = 1 ,2279.3,413.699,415.296,415.518
XS GIS Cut Line= 3
     1680194.980      246416.836     1679637.652      246636.389
     1679375.877      246991.052
#Sta/Elev= 30
       0 1239.89    43.1 1221.48    55.9 1216.37    70.5 1211.34   116.3 1198.00
   196.3 1176.19   413.2 1104.80   436.7 1099.66   445.9 1096.63   464.0 1088.18
   496.4 1068.95   502.5 1065.05   515.3 1055.66   522.2 1052.73   528.0 1050.19
   537.2 1050.04   599.0 1054.06   670.3 1056.12   714.6 1061.00   754.1 1062.20
   773.6 1063.85   803.1 1068.94   832.6 1074.88   847.7 1078.67   891.7 1092.20
   906.4 1095.41   935.9 1100.13   974.9 1108.21  1009.7 1117.32  1039.8 1126.32
#Mann= 3 , 0 , 0
       0     0.1       0   522.2   0.045       0   537.2     0.1       0
Bank Sta=   522.2,   537.2
Exp/Cntr=0.3,0.1

Type RM Length L Ch R = 1 ,1864,387.615,400,411.93
XS GIS Cut Line= 3
     1680014.203      246098.585     1679533.562      246249.735
     1679046.699      246427.904
#Sta/Elev= 30
       0 1175.56    64.1 1156.98   116.3 1143.78   188.6 1123.69   263.3 1098.32
   313.1 1083.17   353.0 1066.75   375.3 1059.20   387.7 1056.48   399.9 1055.39
   466.6 1051.78   496.3 1049.59   499.7 1049.31   511.3 1049.53   525.0 1050.41
   552.1 1050.81   562.9 1051.62   575.5 1054.28   588.2 1059.47   626.1 1082.34
   651.4 1095.91   664.0 1101.91   676.7 1106.83   727.3 1123.19   815.7 1154.98
   841.0 1163.03   866.3 1169.66   930.2 1185.30   992.7 1199.80  1022.3 1207.57
#Mann= 3 , 0 , 0
       0     0.1       0   496.3   0.045       0   511.3     0.1       0
Bank Sta=   496.3,   511.3
Exp/Cntr=0.3,0.1

Type RM Length L Ch R = 1 ,1464,395.344,400,405.093
XS GIS Cut Line= 3
     1680011.543      245987.028     1679515.817      245879.653
     1679017.165      245811.410
#Sta/Elev= 30
       0 1171.89    23.4 1164.28   113.9 1141.65   132.8 1135.18   194.9 1111.64
   242.1 1095.74   278.5 1084.13   290.7 1078.52   315.0 1060.62   327.1 1056.56
   393.5 1053.08   497.2 1046.66   499.7 1046.66   509.3 1046.70   514.7 1047.72
   521.3 1048.84   569.2 1070.02   593.2 1078.97   619.0 1087.56   677.1 1110.71
   761.0 1136.73   787.7 1146.29   808.8 1155.19   844.9 1171.98   892.4 1196.33
   904.8 1203.49   935.2 1222.70   975.7 1247.09   988.7 1253.85  1010.5 1263.95
#Mann= 3 , 0 , 0
       0     0.1       0   499.7   0.045       0   514.7     0.1       0
Bank Sta=   499.7,   514.7
Exp/Cntr=0.3,0.1

Type RM Length L Ch R = 1 ,1064,396.065,400,402.931
XS GIS Cut Line= 3
     1680101.053      245714.319     1679633.802      245505.252
     1679167.279      245329.666
#Sta/Elev= 30
       0 1172.08    26.7 1167.57    71.1 1162.39   123.2 1152.65   131.0 1150.38
   197.5 1123.75   247.2 1106.27   269.4 1097.84   305.3 1082.20   318.3 1076.34
   331.3 1068.20   344.3 1056.94   357.3 1049.63   370.3 1048.34   504.4 1043.59
   513.3 1043.24   519.4 1043.57   564.1 1046.54   576.8 1048.32   589.4 1052.19
   602.1 1058.07   614.8 1066.41   627.5 1073.66   640.2 1079.06   703.6 1103.25
   788.5 1131.95   805.1 1138.10   970.0 1202.71   982.7 1208.21  1010.4 1222.13
#Mann= 3 , 0 , 0
       0     0.1       0   504.4   0.045       0   519.4     0.1       0
Bank Sta=   504.4,   519.4
Exp/Cntr=0.3,0.1

Type RM Length L Ch R = 1 ,664,374.142,359.913,348.063
XS GIS Cut Line= 3
     1680266.105      245457.074     1679853.091      245176.672
     1679405.277      244937.172
#Sta/Elev= 30
       0 1194.37    17.7 1187.68    36.0 1181.53   138.5 1149.01   189.8 1137.04
   292.3 1115.01   334.8 1103.45   386.4 1087.33   407.1 1081.31   421.5 1076.70
   437.7 1069.13   450.2 1061.46   464.5 1051.87   478.9 1045.61   491.7 1042.28
   493.2 1041.91   506.3 1041.33   506.7 1041.35   532.6 1042.93   580.3 1044.69
   630.6 1044.91   743.1 1047.86   830.2 1049.22   857.0 1051.93   884.1 1055.92
   911.0 1060.60   937.9 1066.13   957.9 1068.10   991.8 1069.44  1006.3 1069.59
#Mann= 3 , 0 , 0
       0     0.1       0   491.7   0.045       0   506.7     0.1       0
Bank Sta=   491.7,   506.7
Exp/Cntr=0.3,0.1

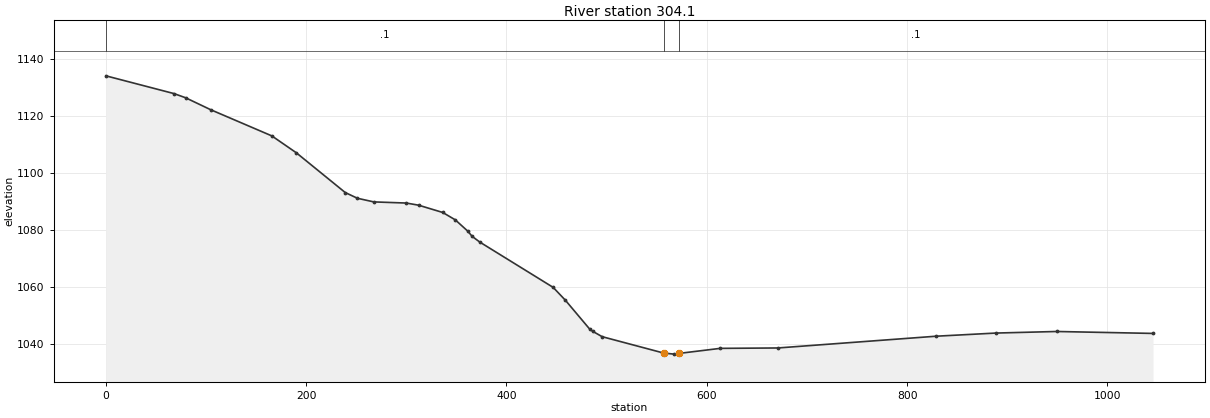
Type RM Length L Ch R = 1 ,304.1,306.806,304.06,301.314
XS GIS Cut Line= 3
     1680482.088      244955.963     1679958.538      244829.297
     1679451.877      244846.186
#Sta/Elev= 30
       0 1134.22    67.9 1128.00    79.5 1126.54   104.6 1122.34   165.7 1113.15
   190.1 1107.24   239.0 1093.28   251.2 1091.27   267.5 1090.00   300.0 1089.60
   312.2 1088.85   336.3 1086.30   348.9 1083.70   361.1 1079.82   365.8 1077.89
   373.3 1075.92   446.6 1060.02   458.8 1055.51   483.3 1045.29   486.3 1044.57
   495.5 1042.73     557 1036.98   567.4 1036.61     572 1036.85   613.4 1038.63
   670.9 1038.77   829.3 1042.90   888.7    1044   949.4 1044.55  1045.6 1043.87
#Mann= 3 , 0 , 0
       0     0.1       0     557   0.045       0     572     0.1       0
Bank Sta=     557,     572
Exp/Cntr=0.3,0.1